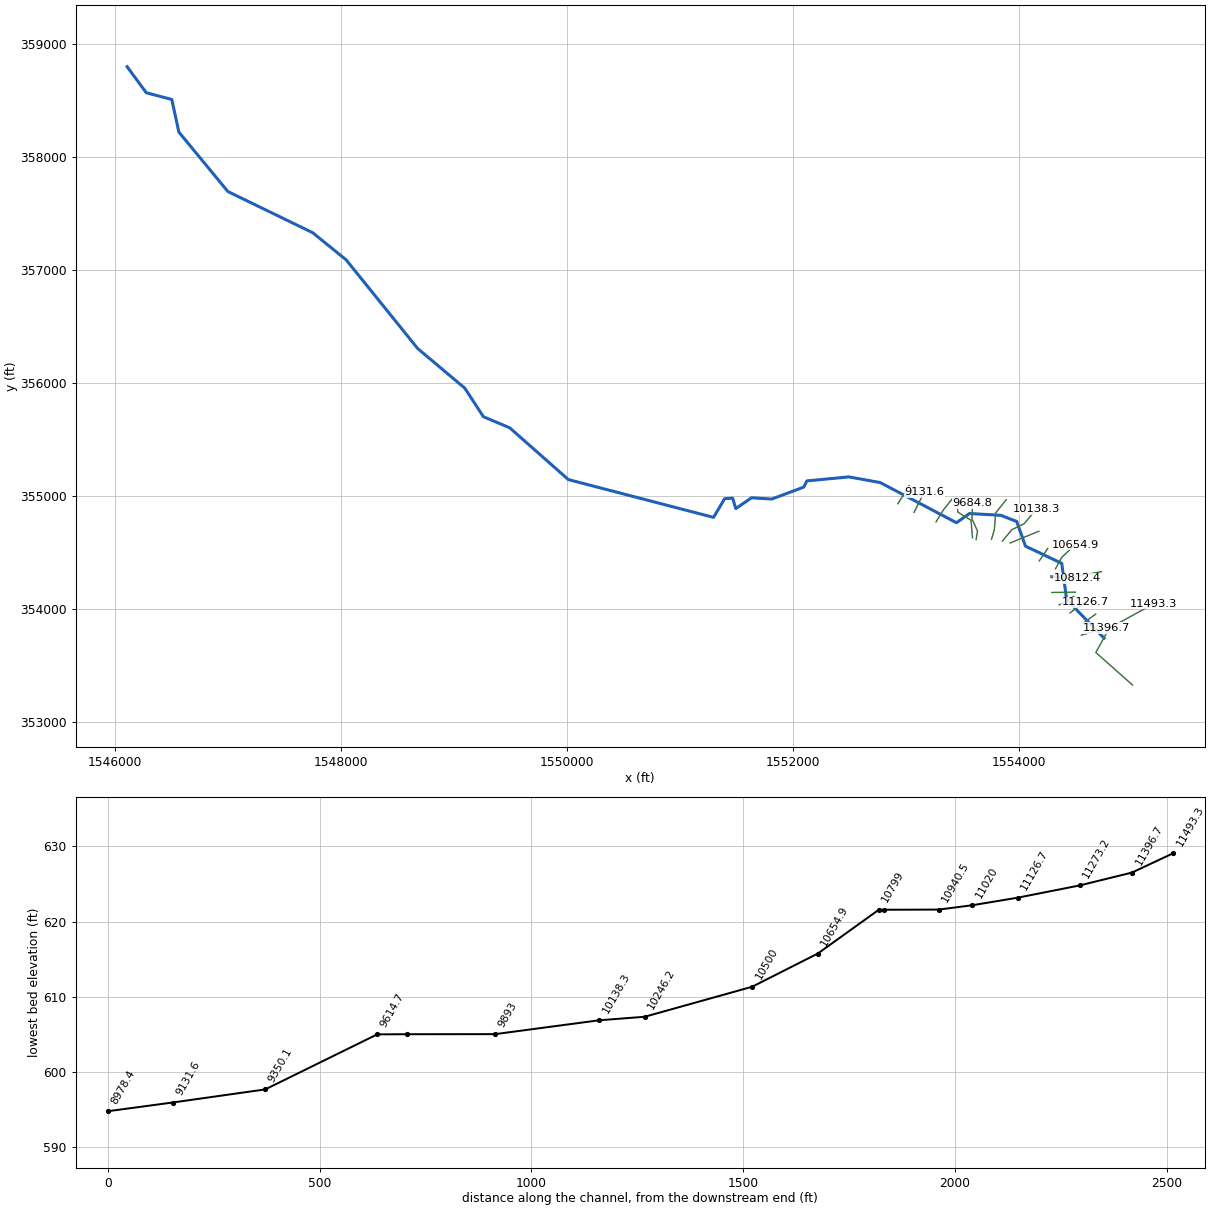
--- DRAGCR.prj (project) ---

Proj Title=DRAGCR
Current Plan=p01
Default Exp/Contr=0,0
English Units
Geom File=g01
Flow File=f01
Plan File=p01
BEGIN DESCRIPTION:
END DESCRIPTION:
DSS Export Rating Curves= 0
DSS Export Rating Curve Sorted= 0
DSS Export Volume Flow Curves= 0
DXF OffsetX= 0
DXF OffsetY= 0
DXF ScaleX= 0
DXF ScaleY= 0

--- DRAGCR.p01 (plan) ---

Plan Title=Floodplain
Program Version=4.00
Geom File=g01
Flow File=f01
K Sum by GR=0
Std Step Tol=0.01
Critical Tol=0.01
Num of Std Step Trials=20
Max Error Tol=0.3
Flow Tol Ratio=0.001
Split Flow NTrial=30
Split Flow Tol=0.02
Split Flow Ratio=0.02
Log Output Level=0
Friction Slope Method=1
Unsteady Friction Slope Method=2
Unsteady Bridges Friction Slope Method=1
Global Log Level=0
CheckData=False
Run HTab=0
Run UNet=0
Run PostProcess=0
UNET Theta=0
UNET Theta Warmup=0
UNET ZTol=0
UNET ZSATol=0
UNET MxIter=0
UNET MaxInSteps=0
UNET DtIC=0
UNET DtMin=0
UNET MaxCRTS=0
UNET WFStab=0
UNET SFStab=0
UNET WFX=0
UNET SFX=0
UNET DSS MLevel=0
UNET DZMax Abort=0
UNET Convert EG Bridges=0
UNET Use Existing IB Tables=0
UNET Froude Limit=0
UNET Froude Power=0
Write IC File=0
Echo Input=False
Echo Output=False
Write Detailed=0

--- DRAGCR.f01 (steady flow) ---

Flow Title=NFF Regression Equation
Program Version=4.00
Number of Profiles= 1
Profile Names=P100yr
River Rch & RM=DRAGCR,Main            ,11493.3
344.2818
River Rch & RM=DRAGCR,Main            ,11396.7
 386.537
River Rch & RM=DRAGCR,Main            ,10799
391.7093
River Rch & RM=DRAGCR,Main            ,10500
610.8613
River Rch & RM=DRAGCR,Main            ,9893
 672.217
Boundary for River Rch & Prof#=DRAGCR,Main            , 1
Up Type= 0
Dn Type= 3
Dn Slope=0.008
DSS Import GetInterval= 0
DSS Import GetPeak= 0
DSS Import FillOption= 0

--- DRAGCR.g01 (geometry) ---

Geom Title=Geometry
Program Version=4.00

River Reach=DRAGCR          ,Main
Reach XY= 30
     1554752.003      353744.386     1554420.688      354085.356
     1554377.404      354405.648     1554056.431      354558.038
     1553978.619      354776.278     1553838.863      354830.645
     1553560.705      354846.815      1553445.46      354765.323
     1552770.155      355120.576     1552492.686        355170.5
     1552121.137      355134.957     1552094.432      355080.612
     1551810.034      354974.423     1551631.918      354986.054
     1551492.047      354890.252     1551464.302      354982.992
     1551393.218      354977.631     1551295.567      354812.306
     1550010.471      355146.692     1549491.172      355604.529
     1549257.782      355703.185     1549094.502      355954.467
     1548675.981      356306.464     1548043.258       357090.29
      1547746.92      357330.427     1546996.377      357694.521
     1546562.677      358220.175     1546499.868      358508.715
     1546274.066      358568.449     1546104.408      358798.606

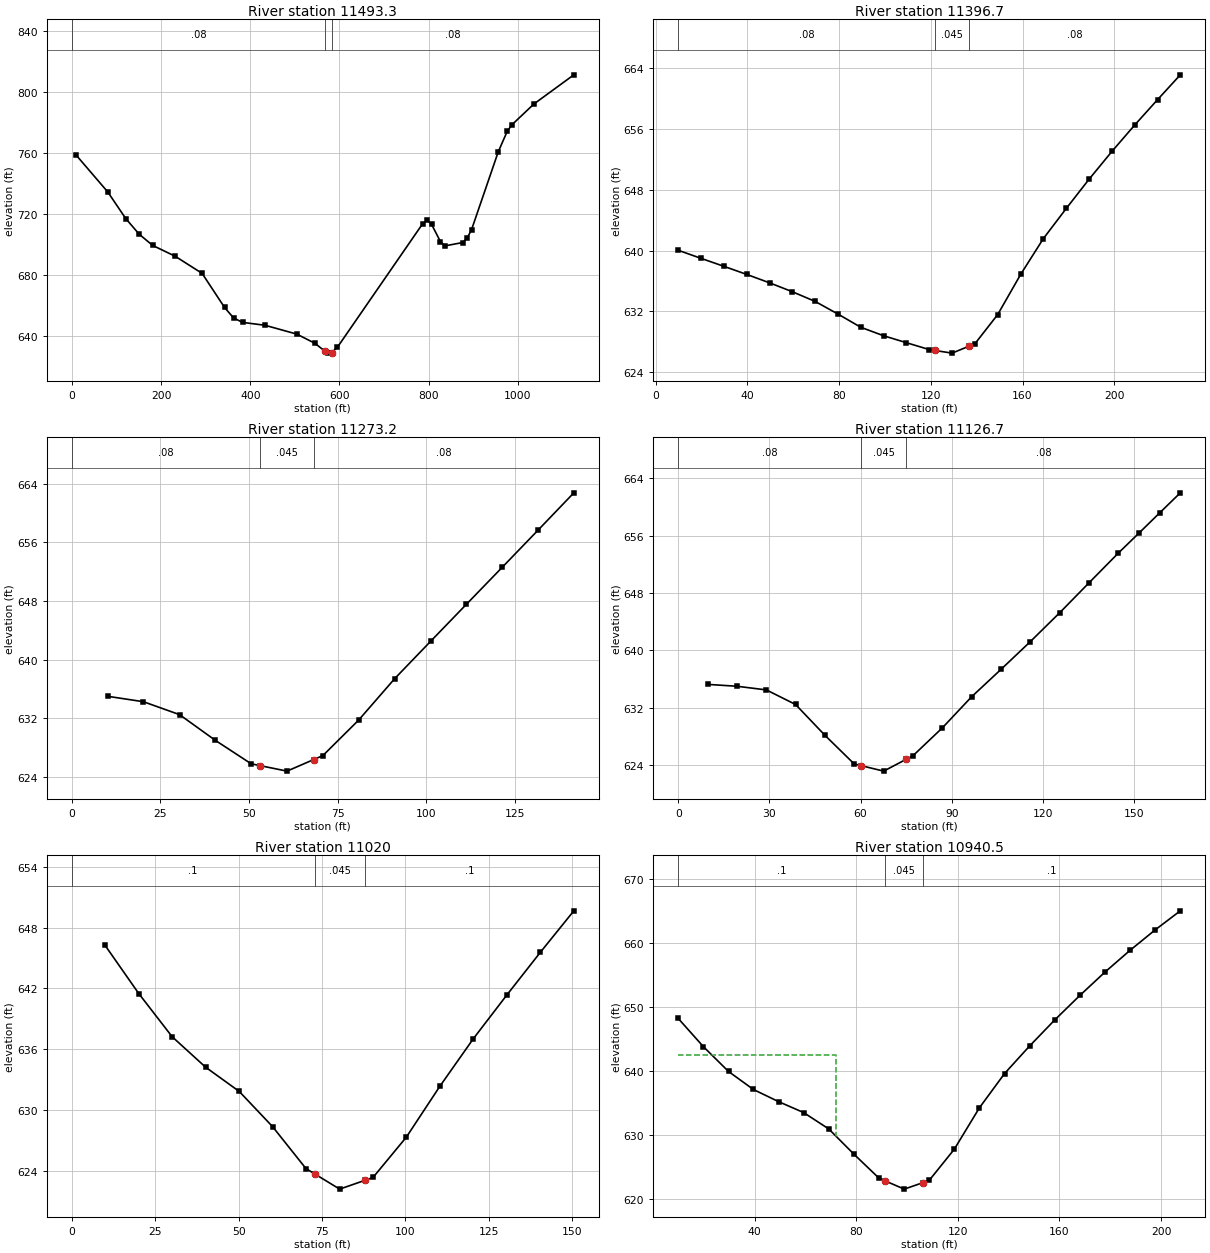
Type RM Length L Ch R = 1 ,11493.3 ,114.6,96.6,78.7
XS GIS Cut Line= 4
     1555003.523      353329.887     1554679.546      353617.296
     1554796.145      353831.203     1555189.284      354047.044
#Sta/Elev= 30
    10.1  758.56    80.6  734.57   120.9  717.16   151.1  706.88   181.3  699.55
   231.7  692.47   292.1  681.25   342.4  658.95   362.6  652.09   382.7  649.18
   433.1  647.29   504.1  641.53   544.7  635.53   567.7  630.26   575.2  629.06
   582.7  629.46   595.5  632.97   786.3  713.73   796.3  716.08   806.3  713.37
   826.2  702.05   836.2  699.25     876  701.43     886  704.26     896   709.9
   955.8  760.82   975.7  774.12   985.7  778.32  1035.5  792.07  1125.2   811.2
#Mann= 3 , 0 , 0
       0     .08       0   567.7    .045       0   582.7     .08       0
Bank Sta=567.7,582.7
XS Rating Curve= 0 ,0
Exp/Cntr=0.3,0.1

Type RM Length L Ch R = 1 ,11396.7 ,115.5,123.5,131.5
XS GIS Cut Line= 2
     1554551.094      353770.743     1554770.879      353834.411
#Sta/Elev= 25
     9.9  640.04    19.9  638.97    29.8  637.93    39.8  636.86    49.7  635.76
    59.7  634.58    69.6  633.31    79.6  631.64    89.5  629.91    99.5  628.79
   109.4  627.88   119.4  626.97   121.8  626.86   129.3  626.51   136.8  627.44
   139.3  627.76   149.2  631.59   159.2  636.87   169.1  641.58   179.1  645.55
     189  649.38     199  653.05   208.9  656.51   218.9  659.86   228.8  663.12
#Mann= 3 , 0 , 0
     9.9     .08       0   121.8    .045       0   136.8     .08       0
Bank Sta=121.8,136.8
XS Rating Curve= 0 ,0
Exp/Cntr=0.3,0.1

Type RM Length L Ch R = 1 ,11273.2 ,146.6,146.5,146.3
XS GIS Cut Line= 2
     1554564.176      353873.658      1554678.43      353957.386
#Sta/Elev= 16
    10.1     635    20.2  634.26    30.4   632.5    40.5  628.99    50.6   625.8
    53.2  625.54    60.7   624.8    68.2  626.37    70.8  626.91    80.9  631.75
    91.1  637.42   101.2  642.49   111.3  647.54   121.4  652.58   131.5  657.64
   141.6  662.73
#Mann= 3 , 0 , 0
       0     .08       0    53.2    .045       0    68.2     .08       0
Bank Sta=53.2,68.2
XS Rating Curve= 0 ,0
Exp/Cntr=0.3,0.1

Type RM Length L Ch R = 1 ,11126.7 ,108.9,106.7,104.5
XS GIS Cut Line= 3
     1554450.795      353967.852     1554567.665      354053.324
     1554586.852      354060.301
#Sta/Elev= 20
     9.7  635.26    19.3     635      29  634.49    38.6  632.46    48.3  628.15
    57.9  624.17    60.1  623.94    67.6  623.17    75.1  624.84    77.2   625.3
    86.9   629.2    96.5  633.52   106.2  637.35   115.8   641.2   125.5  645.24
   135.1  649.39   144.8  653.56   151.6  656.35   158.4  659.16   165.2  661.96
#Mann= 3 , 0 , 0
       0     .08       0    60.1    .045       0    75.1     .08       0
Bank Sta=60.1,75.1
XS Rating Curve= 0 ,0
Exp/Cntr=0.3,0.1

Type RM Length L Ch R = 1 ,11020   ,91.1,79.5,67.7
XS GIS Cut Line= 2
     1554354.857      354037.625     1554484.809      354113.503
#Sta/Elev= 17
      10  646.24    20.1  641.48    30.1  637.22    40.1  634.22    50.2  631.82
    60.2  628.34    70.2   624.2    72.8  623.68    80.3  622.17    87.8  623.03
    90.3  623.32   100.3  627.31   110.4  632.36   120.4  637.04   130.4  641.34
   140.5  645.58   150.5  649.66
#Mann= 3 , 0 , 0
       0      .1       0    72.8    .045       0    87.8      .1       0
Bank Sta=72.8,87.8
XS Rating Curve= 0 ,0
Exp/Cntr=0.3,0.1

Type RM Length L Ch R = 1 ,10940.5 ,128.9,128.2,127.5
XS GIS Cut Line= 2
     1554290.316       354148.39     1554497.892      354151.006
#Sta/Elev= 23
     9.9  648.19    19.8   643.8    29.7  639.93    39.5  637.12    49.4  635.23
    59.3  633.52    69.2  630.96    79.1  627.03      89  623.28    91.4  622.87
    98.9  621.59   106.4  622.62   108.7  622.94   118.6  627.81   128.5  634.27
   138.4  639.61   148.3  643.92   158.2  647.98   168.1   651.8   177.9  655.41
   187.8  658.81   197.7     662   207.6  664.97
#Mann= 3 , 0 , 0
     9.9      .1       0    91.4    .045       0   106.4      .1       0
#XS Ineff= 2 , 0
           72.15  642.51
Permanent Ineff=
       F       F
Bank Sta=91.4,106.4
XS Rating Curve= 0 ,0
Exp/Cntr=0.3,0.1

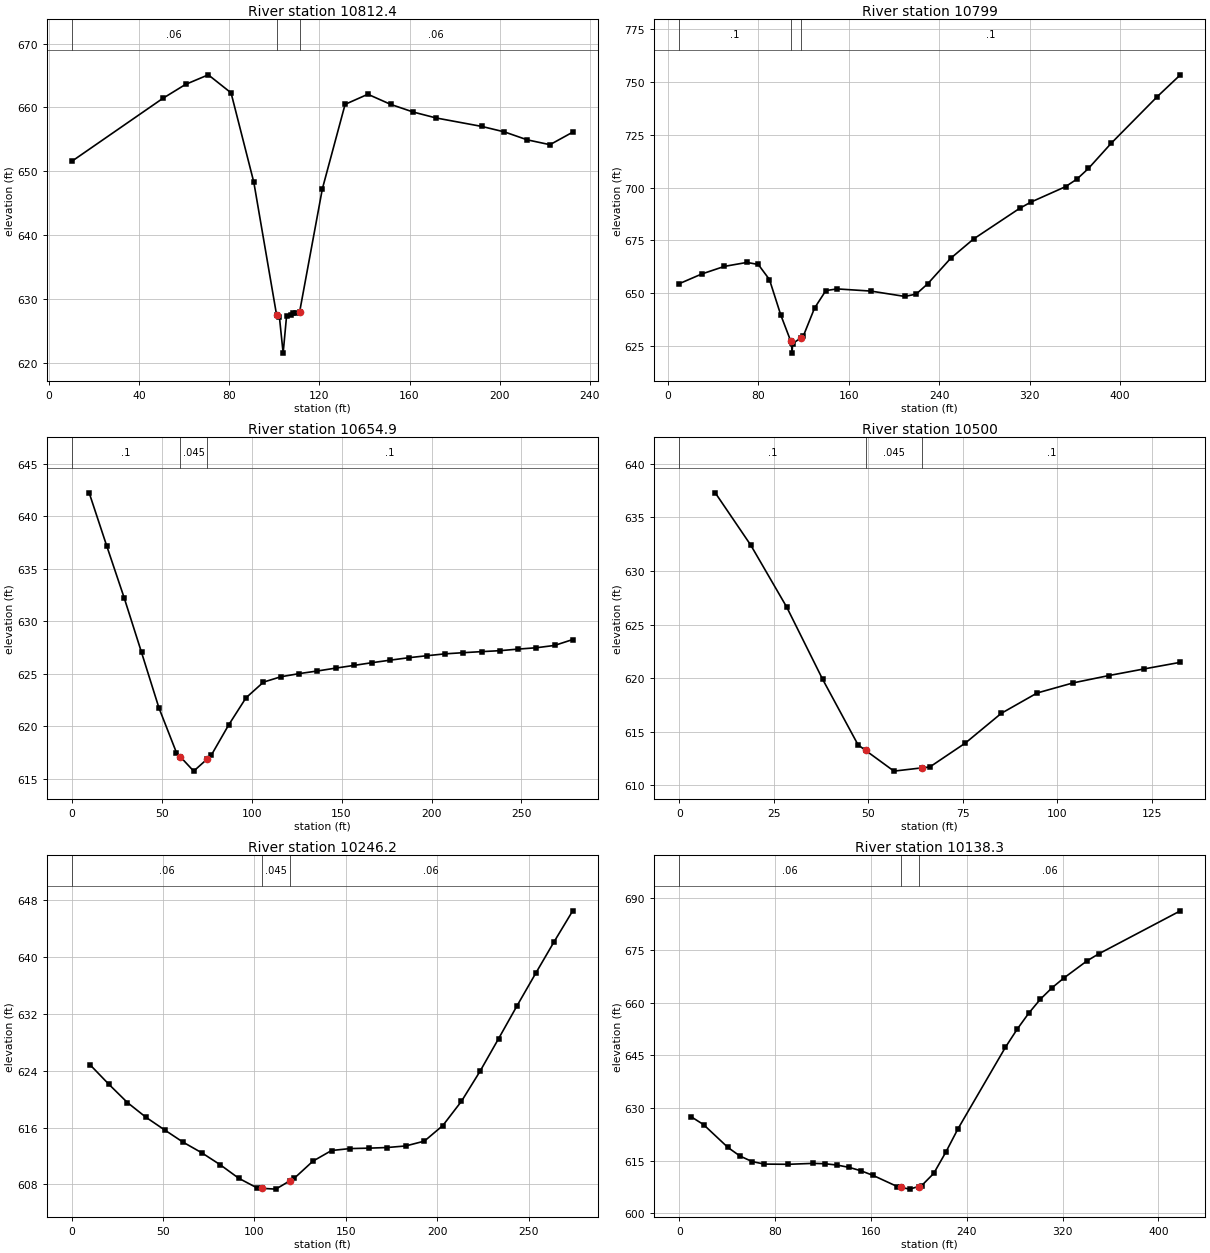
Type RM Length L Ch R = 1 ,10812.4 ,13.5,13.4,13.3
XS GIS Cut Line= 2
     1554283.114        354280.2     1554515.466      354275.017
#Sta/Elev= 25
    10.1  651.57    50.5  661.42    60.6  663.61    70.7  665.11    80.8  662.29
    90.9   648.3     101  627.54  102.23   627.3  103.91  621.57  105.44  627.41
  107.27  627.51   108.5  627.86  109.72  627.82   111.2  627.98   121.3  647.26
   131.4  660.49   141.5  662.07   151.6  660.49   161.7  659.28   171.8  658.36
     192  657.04   202.1  656.18   212.2  654.94   222.3  654.18   232.4  656.14
#Mann= 3 , 0 , 0
    10.1     .06       0     101    .045       0   111.2     .06       0
Bank Sta=101,111.2
XS Rating Curve= 0 ,0
Exp/Cntr=0.3,0.1

Type RM Length L Ch R = 1 ,10799   ,118.5,144,169.6
XS GIS Cut Line= 3
     1554279.244       354293.99     1554488.563      354288.757
     1554728.408      354332.365
#Sta/Elev= 30
      10  654.48    29.9  659.07    49.9  662.66    69.8  664.53    79.8  663.56
    89.7  656.42    99.7  639.65  108.46  627.35  109.24  626.18   109.7  621.56
  110.21   626.1   117.2  628.64   119.6  629.57   129.6   642.9   139.6  651.19
   149.6  651.98   179.5  650.95   209.4  648.42   219.5  649.52   229.7  654.41
     250  666.47   270.3  675.64     311  690.14   321.1  693.13   351.6  700.41
   361.7     704   371.9  709.05   392.2  721.08   432.8  743.09   453.2   753.4
#Mann= 3 , 0 , 0
      10      .1       0  108.46    .045       0   117.2      .1       0
Bank Sta=108.46,117.2
XS Rating Curve= 0 ,0
Exp/Cntr=0.3,0.1

Type RM Length L Ch R = 1 ,10654.9 ,157.1,154.9,152.8
XS GIS Cut Line= 3
     1554321.714      354356.837     1554377.533       354458.88
     1554494.403      354571.389
#Sta/Elev= 30
     9.7  642.22    19.4   637.2    29.1  632.26    38.8  627.04    48.5  621.75
    58.2  617.51    60.3  617.12    67.8  615.74    75.3  616.89    77.5  617.23
    87.2  620.12    96.9  622.72   106.6  624.21   116.3  624.72   126.5  625.02
   136.6  625.27   146.7  625.54   156.9   625.8     167  626.06   177.1   626.3
   187.3  626.53   197.4  626.72   207.6   626.9   217.7  627.01   227.8  627.11
     238   627.2   248.1  627.35   258.3  627.48   268.4   627.7   278.5  628.26
#Mann= 3 , 0 , 0
       0      .1       0    60.3    .045       0    75.3      .1       0
Bank Sta=60.3,75.3
XS Rating Curve= 0 ,0
Exp/Cntr=0.3,0.1

Type RM Length L Ch R = 1 ,10500   ,267.1,253.7,240.4
XS GIS Cut Line= 2
     1554178.679      354427.482     1554252.813      354537.375
#Sta/Elev= 16
     9.5  637.29    18.9  632.41    28.4  626.64    37.9  619.91    47.3  613.78
    49.3  613.26    56.8  611.33    64.3  611.64    66.3  611.72    75.7  613.95
    85.2  616.72    94.7  618.62   104.2  619.56   113.6  620.24   123.1  620.87
   132.6  621.48
#Mann= 3 , 0 , 0
       0      .1       0    49.3    .045       0    64.3      .1       0
Bank Sta=49.3,64.3
XS Rating Curve= 0 ,0
Exp/Cntr=0.3,0.1

Type RM Length L Ch R = 1 ,10246.2 ,106.5,107.9,109.3
XS GIS Cut Line= 2
     1553921.168      354586.229     1554174.968      354690.017
#Sta/Elev= 29
    10.2  624.78    20.3  622.09    30.5  619.51    40.6  617.45    50.8  615.67
    60.9  613.95    71.1  612.46    81.2  610.78    91.4  608.87   101.6  607.49
   104.2  607.45   111.7  607.34   119.2  608.48   121.9  608.89     132  611.27
   142.2  612.77   152.3  613.04   162.5   613.1   172.6  613.19   182.8  613.41
     193  614.09   203.1  616.28   213.3  619.69   223.4  623.88   233.6  628.49
   243.7  633.11   253.9  637.67     264  642.12   274.2  646.47
#Mann= 3 , 0 , 0
       0     .06       0   104.2    .045       0   119.2     .06       0
Bank Sta=104.2,119.2
XS Rating Curve= 0 ,0
Exp/Cntr=0.3,0.1

Type RM Length L Ch R = 1 ,10138.3 ,221.3,245.3,268.7
XS GIS Cut Line= 4
     1553851.952      354602.827     1553936.123      354703.951
     1554045.389      354756.643     1554150.232      354884.536
#Sta/Elev= 30
    10.1  627.45    20.2  625.27    40.5  618.77    50.6  616.31    60.7  614.74
    70.8  614.01    91.1  613.95   111.3  614.21   121.4  614.12   131.6  613.73
   141.7  613.08   151.8  612.08   161.9  610.76   182.1  607.58   184.7  607.39
   192.2  606.87   199.7  607.61   202.3  607.87   212.4  611.36   222.6  617.49
   232.7  624.12   272.3  647.35   282.1   652.5   291.8  657.08   301.5  661.06
   311.2   664.3     321  667.06   340.4  671.97   350.2  673.97   418.3  686.23
#Mann= 3 , 0 , 0
       0     .06       0   184.7    .045       0   199.7     .06       0
Bank Sta=184.7,199.7
XS Rating Curve= 0 ,0
Exp/Cntr=0.3,0.1

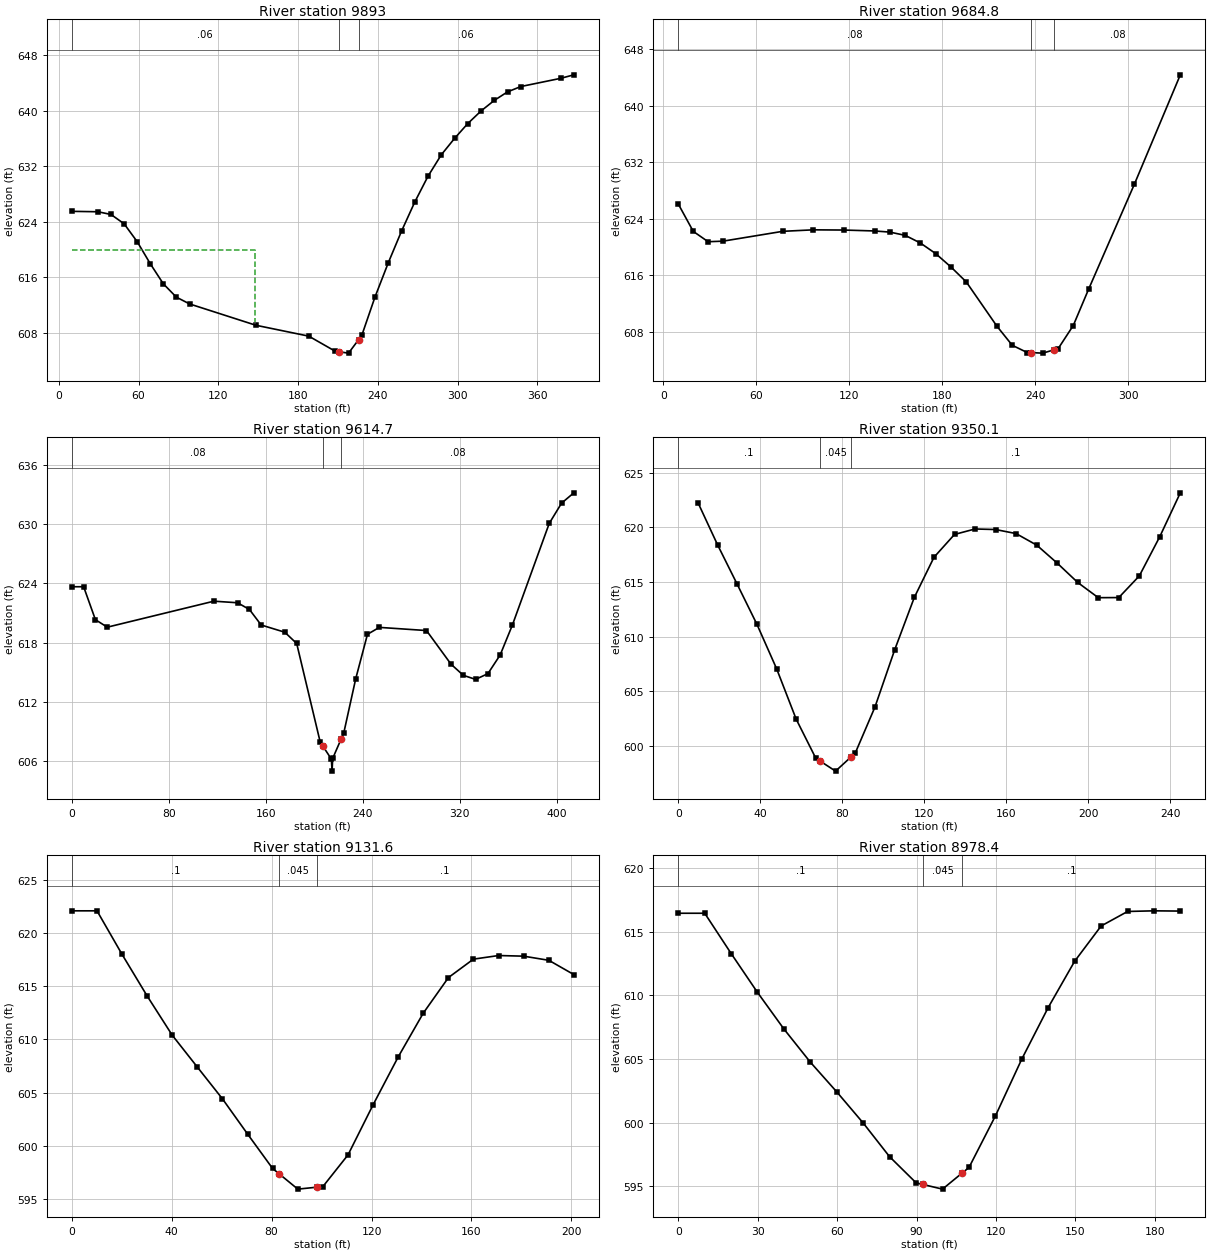
Type RM Length L Ch R = 1 ,9893    ,207.2,208.2,209.8
XS GIS Cut Line= 4
      1553755.47       354618.57     1553780.752      354703.407
     1553792.973       354852.31     1553886.294       354969.18
#Sta/Elev= 30
     9.8  625.48    29.5  625.42    39.3  625.03    49.2  623.68      59  621.11
    68.9  617.91    78.7  615.02    88.5   613.1    98.5  612.12   148.3  609.05
   188.1  607.48     208   605.3   210.5  605.23     218  605.03   225.5  606.95
     228   607.6   237.9  613.12   247.9  618.06   257.9  622.64   267.8  626.81
   277.8  630.55   287.8  633.64   297.8  636.01   307.7  638.14   317.7  639.96
   327.7  641.49   337.6  642.71   347.6  643.48   377.5  644.66   387.5  645.17
#Mann= 3 , 0 , 0
     9.8     .06       0   210.5    .045       0   225.5     .06       0
#XS Ineff= 2 , 0
          147.65  619.93
Permanent Ineff=
       F       F
Bank Sta=210.5,225.5
XS Rating Curve= 0 ,0
Exp/Cntr=0.3,0.1

Type RM Length L Ch R = 1 ,9684.8  ,46.1,70.1,94.2
XS GIS Cut Line= 4
     1553619.426      354615.884     1553631.822       354691.95
     1553582.493      354799.671     1553587.769      354937.731
#Sta/Elev= 25
     9.6   626.1    19.3  622.22    28.9  620.76    38.5  620.84    77.1  622.23
    96.8  622.44   116.6  622.41   136.3  622.28   146.2  622.12   156.1  621.66
   165.9  620.58   175.8  619.08   185.7  617.18   195.5  615.09   215.3  608.83
   225.2  606.13     235  605.09   237.4  605.09   244.9  605.02   252.4   605.5
   254.8  605.64   264.6  608.92   274.5  614.05   304.1  628.91   333.7  644.34
#Mann= 3 , 0 , 0
     9.6     .08       0   237.4    .045       0   252.4     .08       0
Bank Sta=237.4,252.4
XS Rating Curve= 0 ,0
Exp/Cntr=0.3,0.1

Type RM Length L Ch R = 1 ,9614.7  ,308.9,264.6,237.5
XS GIS Cut Line= 4
     1553587.776      354631.256     1553574.233      354787.004
     1553458.147       354858.59     1553445.571      354979.513
#Sta/Elev= 30
       0  623.65     9.8  623.65    19.5  620.32    29.3  619.56   117.3  622.19
   136.8  622.03   146.6  621.35   156.3  619.78   175.8  619.05   185.6  617.91
     205  607.94   207.3  607.51   214.2  606.22   214.8     605  215.29  606.28
   222.3  608.26   224.5  608.89   234.3  614.34     244  618.84   253.8  619.54
   292.7  619.22     313  615.81   323.1  614.69   333.2  614.28   343.4  614.86
   353.5  616.75   363.6  619.78     394  630.06   404.2  632.11   414.3  633.15
#Mann= 3 , 0 , 0
       0     .08       0   207.3    .045       0   222.3     .08       0
Bank Sta=207.3,222.3
XS Rating Curve= 0 ,0
Exp/Cntr=0.3,0.1

Type RM Length L Ch R = 1 ,9350.1  ,216.7,218.5,220.3
XS GIS Cut Line= 3
     1553264.925      354772.528     1553330.195      354878.765
     1553404.861      354972.906
#Sta/Elev= 27
     9.6  622.27    19.2  618.39    28.8  614.77    38.4  611.11      48  607.04
    57.5  602.44    67.1  598.85    69.2   598.6    76.7  597.68    84.2  598.97
    86.3  599.33    95.9  603.54   105.5  608.77   115.1  613.58   124.7  617.26
   134.7  619.35   144.7  619.85   154.7   619.8   164.7  619.43   174.8  618.37
   184.8  616.72   194.8  614.95   204.8  613.56   214.8  613.57   224.8  615.55
   234.8  619.15   244.8  623.16
#Mann= 3 , 0 , 0
       0      .1       0    69.2    .045       0    84.2      .1       0
Bank Sta=69.2,84.2
XS Rating Curve= 0 ,0
Exp/Cntr=0.3,0.1

Type RM Length L Ch R = 1 ,9131.6  ,155.2,153.2,151.3
XS GIS Cut Line= 2
     1553069.954      354857.241     1553161.072      355036.439
#Sta/Elev= 23
       0  622.09    10.1  622.09    20.1  618.01    30.2  614.08    40.2  610.41
    50.3   607.4    60.3  604.43    70.4  601.11    80.4  597.88      83  597.38
    90.5  595.94      98  596.12   100.5  596.17   110.6  599.16   120.6  603.85
   130.7  608.37   140.7  612.47   150.8  615.82   160.8  617.55   170.9  617.89
   180.9  617.83     191  617.44     201   616.1
#Mann= 3 , 0 , 0
       0      .1       0      83    .045       0      98      .1       0
Bank Sta=83,98
XS Rating Curve= 0 ,0
Exp/Cntr=0.3,0.1

Type RM Length L Ch R = 1 ,8978.4  ,8953.7,8978.4,8975.2
XS GIS Cut Line= 2
     1552927.202      354933.172     1553027.432      355094.147
#Sta/Elev= 22
       0  616.45      10  616.45      20  613.28    29.9  610.24    39.9  607.36
    49.9  604.75    59.9  602.41    69.9  599.96    79.8  597.33    89.8  595.28
    92.3  595.15    99.8  594.78   107.3  596.06   109.8  596.48   119.8  600.54
   129.7  604.98   139.7  609.04   149.7  612.68   159.7  615.45   169.7  616.59
   179.6  616.64   189.6  616.62
#Mann= 3 , 0 , 0
       0      .1       0    92.3    .045       0   107.3      .1       0
Bank Sta=92.3,107.3
XS Rating Curve= 0 ,0
Exp/Cntr=0.3,0.1

Chan Stop Cuts=-1
Use User Specified Reach Order=0